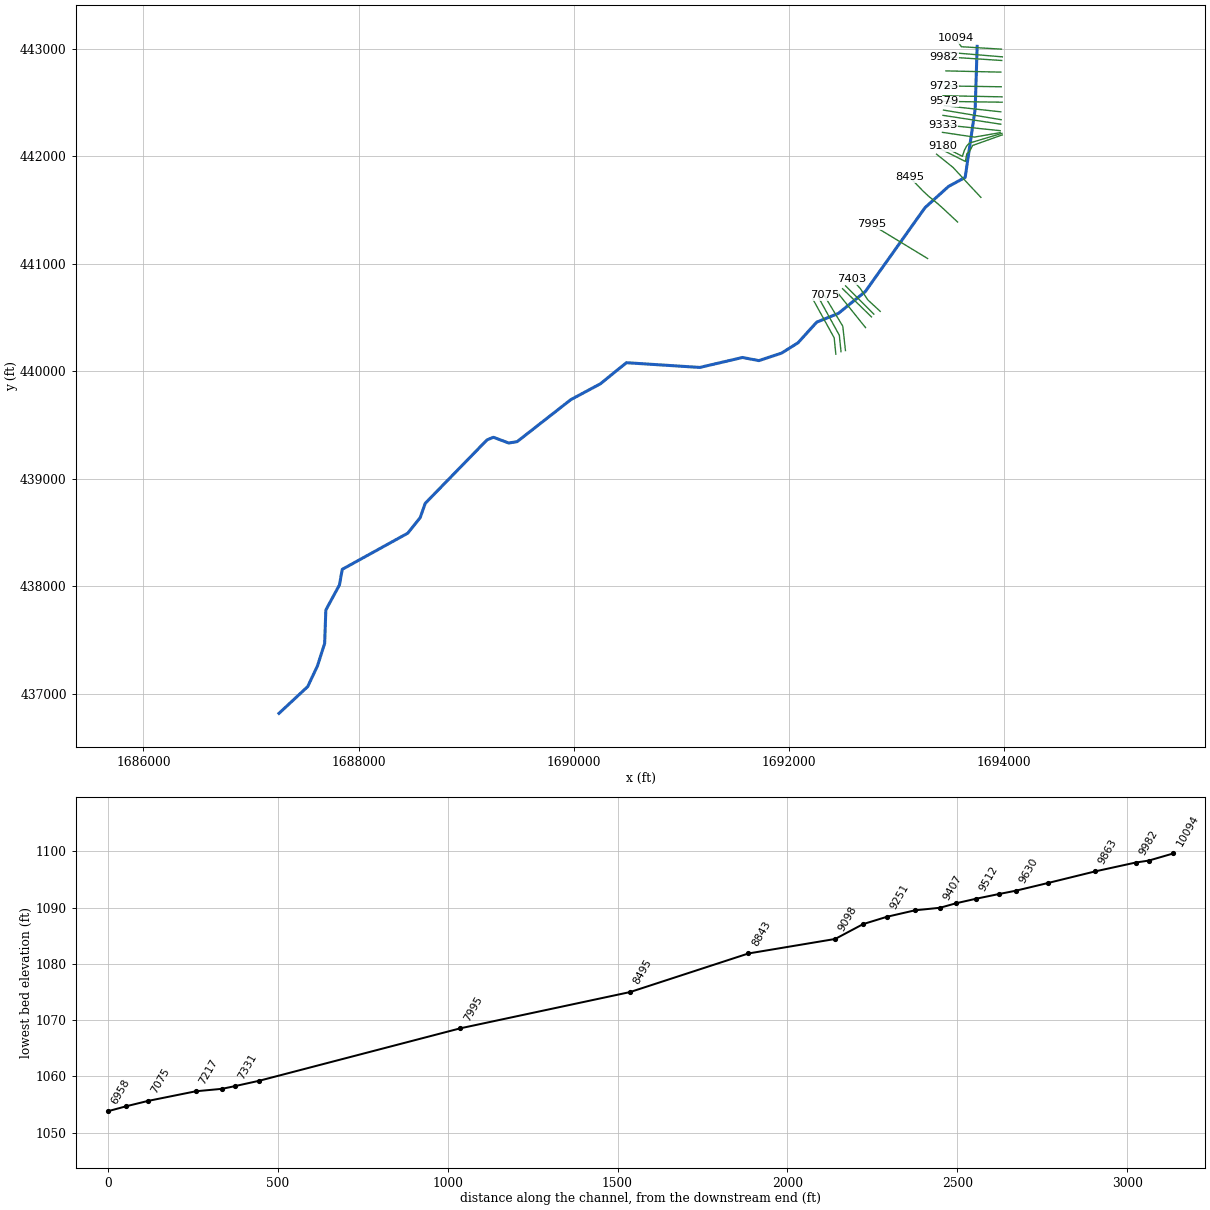
--- BROWNSRN.prj (project) ---

Proj Title=BROWNSRN
Current Plan=p01
Default Exp/Contr=0,0
English Units
Geom File=g01
Flow File=f01
Plan File=p01
BEGIN DESCRIPTION:
---------- MODELED AS PART OF WVEMD CTP PROGRAM, 2023----------
Stream Name: Browns Run
Flood Zone:  AFH
Wetzel County, WV
HEC-RAS Version: RAS 6.3
Vertical Datum: NAVD88
Projection: NAD 1983 StatePlane West Virginia S FIPS 4702 (US Feet)
Terrain: 1-meter West Virginia FEMA R3 South Central (collected 2018-2020)
Land Use: 2019 NLCD
Hydrologic Method:
WV SIR2010-5033 regression equations
Additional Model Notes:
None
END DESCRIPTION:
DSS Export Rating Curves= 0
DSS Export Rating Curve Sorted= 0
DSS Export Volume Flow Curves= 0
DXF OffsetX= 0
DXF OffsetY= 0
DXF ScaleX= 0
DXF ScaleY= 0

--- BROWNSRN.p01 (plan) ---

Plan Title=Floodplain
Program Version=6.30
Short Identifier=Floodplain
Geom File=g01
Flow File=f01
Subcritical Flow
K Sum by GR= 0
Std Step Tol= 0.01
Critical Tol= 0.01
Num of Std Step Trials= 20
Max Error Tol= 0.3
Flow Tol Ratio= 0.001
Split Flow NTrial= 30
Split Flow Tol= 0.02
Split Flow Ratio= 0.02
Log Output Level= 0
Friction Slope Method= 1
Unsteady Friction Slope Method= 2
Unsteady Bridges Friction Slope Method= 1
Parabolic Critical Depth
Global Vel Dist= 0 , 0 , 0
Global Log Level= 0
CheckData=True
Encroach Param=-1 ,0,0, 0
Mapping Interval=1HOUR
Computation Time Step Use Courant=        0
Computation Time Step Use Time Series=    0
Computation Time Step Count To Double=0
Computation Time Step Max Doubling=0
Computation Time Step Max Halving=0
Computation Time Step Residence Courant=0
Run HTab= 0
Run UNet= 0
Run Sediment= 0
Run PostProcess= 0
Run WQNet= 0
Run RASMapper= 0
UNET Theta= 0
UNET Theta Warmup= 0
UNET ZTol= 0
UNET ZSATol= 0
UNET MxIter= 0
UNET Max Iter WO Improvement= 0
UNET MaxInSteps= 0
UNET DtIC= 0
UNET DtMin= 0
UNET MaxCRTS= 0
UNET WFStab= 0
UNET SFStab= 0
UNET WFX= 1
UNET SFX= 1
UNET Gravity=32.17405
UNET 1D Methodology=Finite Difference
UNET DSS MLevel= 1
UNET Pardiso=0
UNET DZMax Abort= 0
UNET Use Existing IB Tables= 0
UNET Froude Reduction=False
UNET Froude Limit= 0
UNET Froude Power= 0
UNET D1 Cores= 0
UNET WindReference=Eulerian
UNET WindDragFormulation=Hsu (1988)
UNET D2 Coriolis=0
UNET D2 Cores= 0
UNET D2 Theta= 1
UNET D2 Theta Warmup= 1
UNET D2 Z Tol= 0.01
UNET D2 Volume Tol= 0.01
UNET D2 Max Iterations= 20
UNET D2 Equation= 0
UNET D2 RampUpFraction=0.1
UNET D2 TimeSlices= 1
UNET D2 Turbulence Formulation=Non-Conservative (original)
UNET D2 Eddy Viscosity=0.3
UNET D2 Transverse Eddy Viscosity=0.1
UNET D2 Smagorinsky Mixing=0
UNET D2 BCVolumeCheck=0
UNET D2 Cores=0
UNET D2 SolverType=PARDISO (Direct)
UNET D2 Minimum Iterations= 3
UNET D2 Maximum Iterations= 30
UNET D2 Restart Number= 10
UNET D2 Relaxation Coeff=1.3
UNET D2 SOR Precondition Iterations= 10
UNET D2 ILUT Maximum Fill= 8
UNET D2 ILUT Tolerance=1E-08
UNET D2 Convergence Tolerance=0.00001
UNET D1D2 MaxIter= 0
UNET D1D2 ZTol=0.01
UNET D1D2 QTol=0.1
UNET D1D2 MinQTol=1
Write IC File= 0
Write IC File at Fixed DateTime=0
Write IC File at Sim End=0
Echo Input=False
Echo Parameters=False
Echo Output=False
Write Detailed= 0
HDF Write Warmup=0
HDF Write Time Slices=0
HDF Flush=0
HDF Compression= 1
HDF Chunk Size= 1
HDF Spatial Parts= 1
HDF Use Max Rows=0
HDF Fixed Rows= 1
Calibration Method= 0
Calibration Iterations= 20
Calibration Max Change=0.05
Calibration Tolerance=0.2
Calibration Maximum=1.5
Calibration Minimum=0.5
Calibration Optimization Method= 1
WQ AD Non Conservative
WQ ULTIMATE=-1
WQ Max Comp Step=1HOUR
WQ Output Interval=15MIN
WQ Output Selected Increments= 0
WQ Output face flow=0
WQ Output face velocity=0
WQ Output face area=0
WQ Output face dispersion=0
WQ Output cell volume=0
WQ Output cell surface area=0
WQ Output cell continuity=0
WQ Output cumulative cell continuity=0
WQ Output face conc=0
WQ Output face dconc_dx=0
WQ Output face courant=0
WQ Output face peclet=0
WQ Output face adv mass=0
WQ Output face disp mass=0
WQ Output cell mass=0
WQ Output cell source sink temp=0
WQ Output nsm pathways=0
WQ Output nsm derived pathways=0
WQ Create Restart=0
WQ Fixed Restart=0
WQ System Summary=0
WQ Write To DSS=0
Sorting and Armoring Iterations= 10
XS Update Threshold= 0.02
Bed Roughness Predictor= 0
Hydraulics Update Threshold= 0.02
Energy Slope Method= 1
Volume Change Method= 1
Sediment Retention Method= 0
Sediment TS Multiplier= 1
Warm Up Method= 0
XS Weighting Method= 0
Number of US Weighted Cross Sections= 1
Number of DS Weighted Cross Sections= 1
Upstream XS Weight=0
Main XS Weight=1
Downstream XS Weight=0
Number of DS XS's Weighted with US Boundary= 1
Upstream Boundary Weight= 1
Weight of XSs Associated with US Boundary= 0
Number of US XS's Weighted with DS Boundary= 1
Downstream Boundary Weight= 0.5
Weight of XSs Associated with DS Boundary= 0.5
Percentile Method= 0
Sediment Output Level= 3
Mass or Volume Output= 0
Output Increment Type= 1
Profile and TS Output Increment= 1
Transport Output Increment 1
XS Output Flag= 0
XS Output Increment= 10
Read HDF5 Sediment Hotstart= 0
Sediment Hotstart Type= 0
Write Gradation File= 0
Read Gradation Hotstart= 0
Write HDF5 File= 1
Write Binary Output= 1
Write DSS Sediment File= 0
DSS Sediment Output Type= 1
SV Curve= 0
Specific Gage Flag= 0
Subcell Erosion Methods= 0
Subcell Deposition Methods= 0
Advection Scheme= 1
Matrix Solver= 0
Implicit Weighting Factor= 1
Maximum Outer Loop Convergence Iterations= 5
Convergence Maximum Absolute= 0.001
Convergence RMSE= 0.0001
Grain Fractions Max Abs Error= 0.001
Max Subgrid Regions= 1
Max Subgrid Length Scale= 3.402823E+38
Initial Layer Thickness= 3.402823E+38
Min Layer Thickness= 3.402823E+38
Max Layer Thickness= 3.402823E+38
Number of Layers= 5

--- BROWNSRN.f01 (steady flow) ---

Flow Title=Flow
Program Version=4.00
Number of Profiles=1
Profile Names=F01pct
River Rch & RM=BROWNSRN,Main,10094
     629
River Rch & RM=BROWNSRN,Main,7995
     715
River Rch & RM=BROWNSRN,Main,5499
     843
River Rch & RM=BROWNSRN,Main,2998
     993
Boundary for River Rch & Prof#=BROWNSRN,Main      ,1
Up Type=0
Dn Type=3
Dn Slope=0.014857

--- BROWNSRN.g01 (geometry) ---

Geom Title=Geometry
Program Version=6.31

River Reach=BROWNSRN        ,Main
Reach XY= 30
     1693752.062      443024.723     1693733.716      442441.912
     1693640.705      441805.341     1693485.829       441721.29
     1693267.381      441524.1751692712.36351908440743.551577101
 1692461.0427313 440539.56378932      1692260.26       440458.63
1692086.17780763440266.405961835     1691933.602      440170.637
     1691722.274      440100.639     1691570.945      440129.971
     1691173.622      440037.307     1690490.973      440081.306
     1690248.312      439884.644     1689973.653      439737.315
     1689475.666      439347.325     1689397.668      439333.992
     1689254.338      439387.324     1689195.006      439363.324
     1688620.828      438773.219     1688573.043      438639.147
     1688458.085      438495.244     1687848.889      438158.835
     1687822.948       438013.84     1687696.248      437780.101
     1687685.326      437469.633     1687618.699      437261.015
1687527.71902629437067.723951328     1687260.477      436818.658

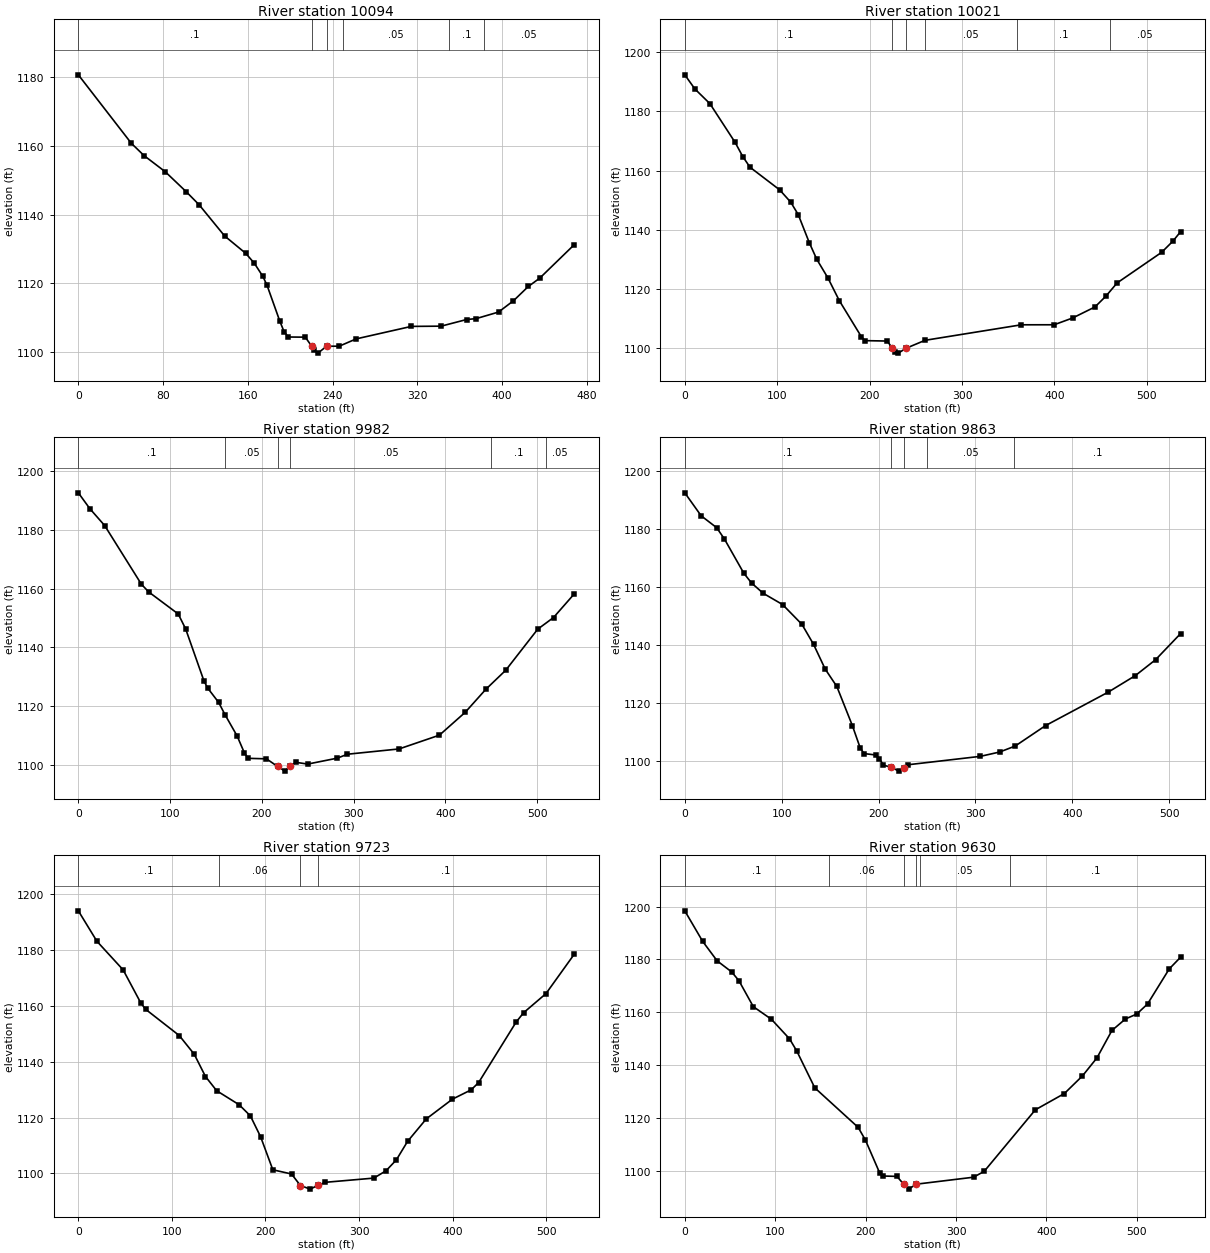
Type RM Length L Ch R = 1 ,10094   ,72.3,72.9,71.8
BEGIN DESCRIPTION:
Structure XS 4
END DESCRIPTION:
XS GIS Cut Line= 3
1693977.97718762442998.4995359881693605.45136383443021.205871914
1693551.52381601 443099.25890166
#Sta/Elev= 30
       0 1180.76      50 1160.82      62 1157.23      82 1152.53   102.1 1146.62
   114.1 1142.86   138.1  1133.8   158.2 1128.69   166.2 1125.82   174.2 1122.03
   178.2 1119.38   190.2 1108.98   194.2 1105.93   198.2 1104.35   214.3  1104.3
  220.271101.676   222.3 1100.54   226.3 1099.65   234.3 1101.66   246.3 1101.67
   262.3  1103.8   314.4 1107.44   342.5 1107.51   366.5 1109.44   375.6 1109.71
   396.7 1111.62   410.8 1114.91   424.8 1119.07   435.6  1121.5   468.1 1131.23
#Mann= 6 ,-1,0
       0      .1       0  220.27    .045       0   234.3      .1       0
     250     .05       0     350      .1       0  383.22     .05       0
Bank Sta=220.27,234.3
XS Rating Curve= 0 ,0
Exp/Cntr(USF)=0,0
Exp/Cntr=0.3,0.1

Type RM Length L Ch R = 1 ,10021   ,38.4,38.7,38.9
BEGIN DESCRIPTION:
Structure XS 3
END DESCRIPTION:
XS GIS Cut Line= 2
1693986.45126626442927.0623614021693451.67250355442971.384905341
#Sta/Elev= 30
       0 1192.38    10.9 1187.61    27.2 1182.63    54.5 1169.53    62.8 1164.73
    70.6 1161.16   102.7 1153.51   114.7 1149.34   122.8 1145.14   134.8 1135.63
   142.8 1130.08   154.9 1123.76   167.2 1116.11     191 1103.95     195 1102.59
   219.1 1102.45  224.761099.953   227.1 1098.76   231.1 1098.37   239.2 1099.98
     260  1102.7   364.2 1107.94   399.7 1107.95   419.8 1110.25   443.9 1113.97
   455.7  1117.6   467.9 1122.09   516.1 1132.43   528.1 1136.15   536.6 1139.39
#Mann= 6 ,-1,0
       0      .1       0  224.76    .045       0   239.2      .1       0
     260     .05       0     360      .1       0     460     .05       0
Bank Sta=224.76,239.2
XS Rating Curve= 0 ,0
Exp/Cntr(USF)=0,0
Exp/Cntr=0.3,0.1

Type RM Length L Ch R = 1 ,9982    ,118.5,118.8,119
BEGIN DESCRIPTION:
Structure XS 2
END DESCRIPTION:
XS GIS Cut Line= 2
1693980.72816513442893.1877467141693441.69196443442928.285841683
#Sta/Elev= 30
       0  1192.5    12.6  1187.1    28.7 1181.39    68.8 1161.42    76.8 1158.82
   108.8 1151.38   116.9 1146.32   136.9 1128.61   140.9 1126.23   152.9 1121.34
     160 1117.07     173 1109.96     181 1104.15     185 1102.37     205 1102.19
   217.1  1099.6   225.1 1098.02  230.341099.618   237.1    1101     250 1100.42
   282.2 1102.43   293.2 1103.76   349.4 1105.55   393.4 1110.23   421.5 1117.99
     444 1125.81   465.6 1132.25   500.5 1146.21   517.7 1150.16   540.2 1158.15
#Mann= 6 ,-1,0
       0      .1       0     160     .05       0   217.1    .045       0
  230.34     .05       0     450      .1       0     510     .05       0
Bank Sta=217.1,230.34
XS Rating Curve= 0 ,0
Exp/Cntr(USF)=0,0
Exp/Cntr=0.3,0.1

Type RM Length L Ch R = 1 ,9863    ,139.6,140,140.5
BEGIN DESCRIPTION:
Structure XS 1
END DESCRIPTION:
XS GIS Cut Line= 2
1693973.01017664442784.918063685 1693461.4080453442796.271231648
#Sta/Elev= 30
       0 1192.36    16.9 1184.44    32.9 1180.34    40.9 1176.44    60.9 1164.66
    68.9 1161.28    80.9 1157.74   100.9 1153.86   120.9 1147.03   132.9 1140.13
   144.9 1131.61   156.9 1125.62   172.9 1112.17   180.9 1104.56   184.9  1102.5
   196.9 1102.02   200.9 1100.76   204.9 1098.53   212.9 1097.78     221 1096.45
   226.4  1097.7   230.4 1098.65     305 1101.54     325 1103.04     341  1105.1
   372.3 1112.14     437 1123.68     465 1129.38   485.9 1134.86   511.7 1143.86
#Mann= 5 ,-1,0
       0      .1       0   212.9    .045       0   226.4      .1       0
     250     .05       0     340      .1       0
Bank Sta=212.9,226.4
XS Rating Curve= 0 ,0
Exp/Cntr(USF)=0,0
Exp/Cntr=0.3,0.1

Type RM Length L Ch R = 1 ,9723    ,92.9,93.1,93.2
BEGIN DESCRIPTION:
Structure XS 4
END DESCRIPTION:
XS GIS Cut Line= 2
1693976.00340156442648.6075455631693446.01369341442656.491689982
#Sta/Elev= 30
       0 1194.08    19.9 1183.16    47.9 1172.92    66.8 1161.06    71.9 1158.81
   107.9 1149.39   123.9  1142.7   135.9 1134.72   147.9 1129.62   171.9  1124.6
   183.9 1120.62   194.9 1113.08   207.9  1101.3   227.9 1099.79  237.361095.667
   247.9 1094.37   255.8 1095.69   263.9 1096.81   315.9 1098.32   328.9 1100.95
   339.9 1104.83   351.9 1111.46   371.9 1119.52   399.9 1126.61   419.9 1129.94
   427.9 1132.56   467.9 1154.18   475.9 1157.56   499.9 1164.43     530 1178.49
#Mann= 4 ,-1,0
       0      .1       0     150     .06       0  237.36    .045       0
   255.8      .1       0
Bank Sta=237.36,255.8
XS Rating Curve= 0 ,0
Exp/Cntr(USF)=0,0
Exp/Cntr=0.3,0.1

Type RM Length L Ch R = 1 ,9630    ,51.2,51.3,51.3
BEGIN DESCRIPTION:
Structure XS 3
END DESCRIPTION:
XS GIS Cut Line= 2
1693983.88754598442554.8738285841693435.50150085442565.386021143
#Sta/Elev= 30
       0 1198.37    19.8 1186.79    35.8 1179.43    51.8 1175.25    59.8 1171.97
    75.8 1162.09    95.8 1157.32   115.8 1149.94   123.8 1145.35   143.8 1131.37
   191.8 1116.39   199.8  1111.6   215.8 1098.98   219.8 1097.98   234.7 1097.84
  242.021094.918   247.8 1093.02   255.8 1094.88   319.4 1097.53   331.2 1099.75
   387.8 1123.05   419.9 1129.21   439.9 1135.88   455.9 1142.68   472.5 1153.08
   487.5 1157.45   499.9 1159.28   511.9  1163.1   535.9 1176.38   548.5 1180.83
#Mann= 6 ,-1,0
       0      .1       0     160     .06       0  242.02    .045       0
   255.8     .06       0     260     .05       0     360      .1       0
Bank Sta=242.02,255.8
XS Rating Curve= 0 ,0
Exp/Cntr(USF)=0,0
Exp/Cntr=0.3,0.1

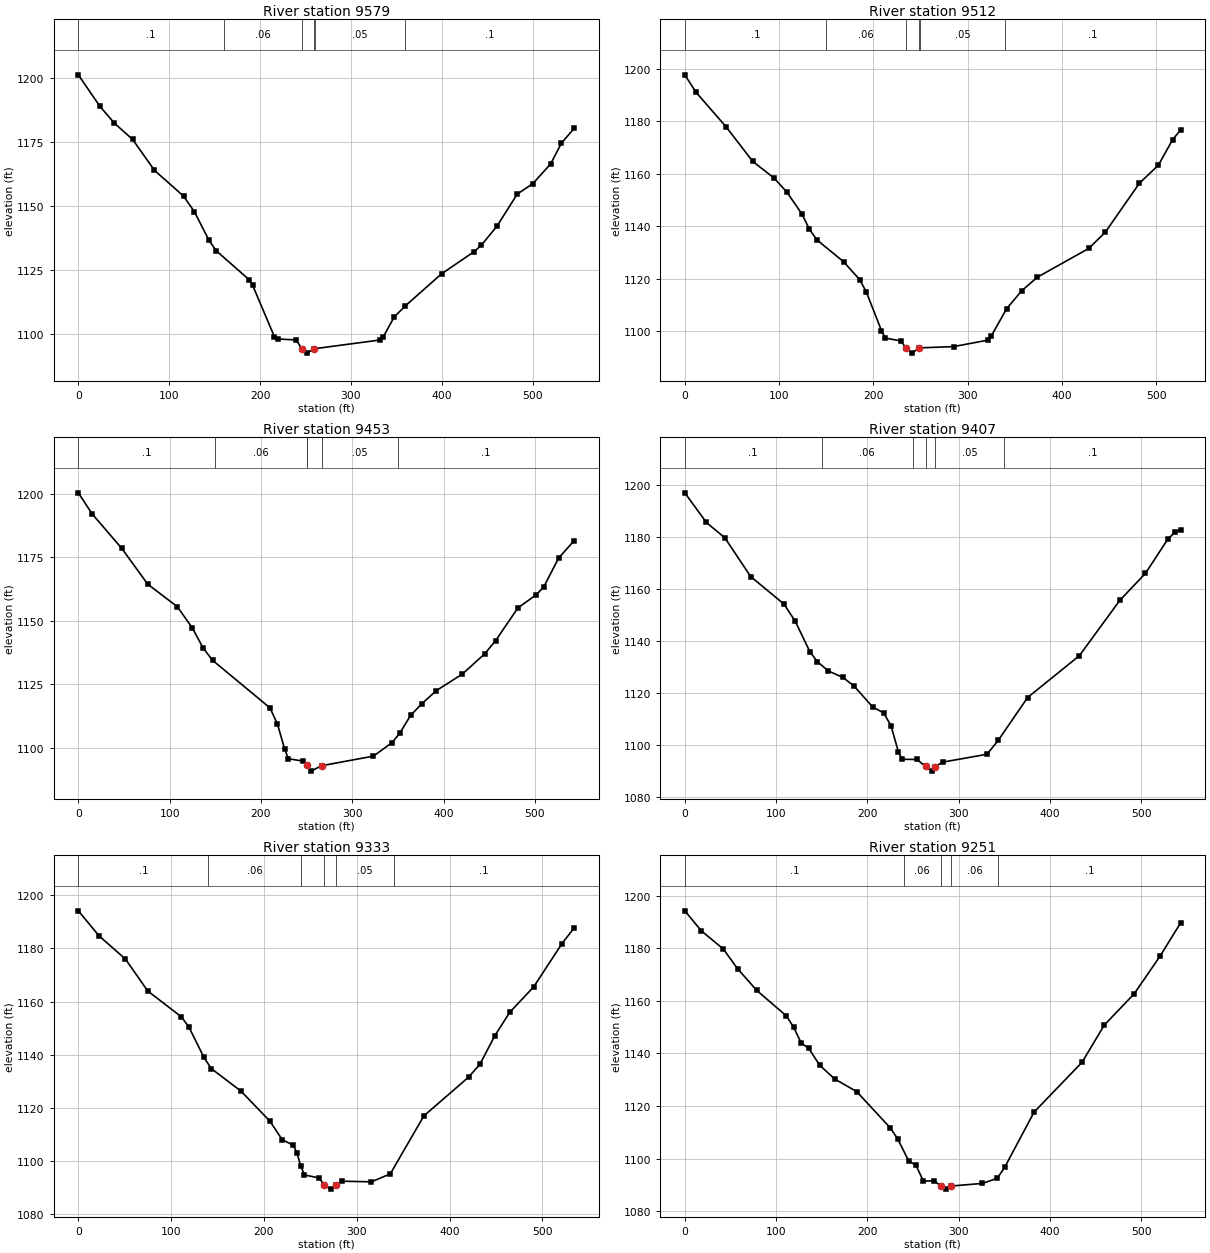
Type RM Length L Ch R = 1 ,9579    ,67.7,67.4,66.3
BEGIN DESCRIPTION:
Structure XS 2
END DESCRIPTION:
XS GIS Cut Line= 2
1693983.88754598442504.9409139321693438.12954899442512.825058351
#Sta/Elev= 30
       0 1201.28    23.8 1188.92    39.8 1182.33    59.8 1175.99    83.8 1163.92
   115.8 1153.83   127.8 1147.71   143.8 1136.56   151.8 1132.45   187.8 1121.21
   191.8 1119.01   215.8 1098.85   219.8 1097.93   239.7 1097.57  246.161094.121
   251.8 1092.41   259.8 1094.13   331.8 1097.53   335.8 1098.91   347.8  1106.6
   359.8 1110.83   399.8 1123.43   435.8 1132.13   443.8 1134.69   460.8 1142.06
   483.2 1154.65   500.2 1158.67   519.8 1166.38   531.8 1174.55   545.8 1180.34
#Mann= 6 ,-1,0
       0      .1       0     160     .06       0  246.16    .045       0
   259.8     .06       0     260     .05       0     360      .1       0
Bank Sta=246.16,259.8
XS Rating Curve= 0 ,0
Exp/Cntr(USF)=0,0
Exp/Cntr=0.3,0.1

Type RM Length L Ch R = 1 ,9512    ,58.6,58.4,57.8
BEGIN DESCRIPTION:
Structure XS 4 AND Structure XS 1
END DESCRIPTION:
XS GIS Cut Line= 2
1693971.62332133442415.5872771871693448.64174155442472.528320211
#Sta/Elev= 30
       0 1197.72    11.9 1191.06    43.8  1177.9    71.9 1164.76    94.8 1158.32
   108.1 1153.06   124.2 1144.71   132.3 1138.76   140.3 1134.72   168.5 1126.42
   185.5 1119.64   192.6 1114.91   208.7 1100.14   212.8 1097.31   228.9 1096.25
  234.621093.707   240.9 1091.57     249 1093.58   285.2 1094.06   321.4 1096.51
   325.4 1098.23   341.5 1108.54   357.6 1115.39   374.2 1120.56   428.6 1131.49
   446.1 1137.65   482.3 1156.34   502.5 1163.27   517.6 1172.98   526.1 1176.74
#Mann= 6 ,-1,0
       0      .1       0     150     .06       0  234.62    .045       0
     249     .06       0     250     .05       0     340      .1       0
Bank Sta=234.62,249
XS Rating Curve= 0 ,0
Exp/Cntr(USF)=0,0
Exp/Cntr=0.3,0.1

Type RM Length L Ch R = 1 ,9453    ,46.8,46.4,46.1
BEGIN DESCRIPTION:
Structure XS 3
END DESCRIPTION:
XS GIS Cut Line= 2
1693975.04211324442342.2595857461693439.31449998442431.665783455
#Sta/Elev= 30
       0 1200.28    15.1    1192    47.6 1178.41      76 1164.34   108.4 1155.48
   124.6 1147.25   136.8 1139.17     147 1134.39   209.8  1115.7   217.9 1109.51
     226 1099.47   230.1 1095.64   246.3  1094.7   250.3 1093.01   254.7 1090.77
   266.6 1092.91   323.3 1096.68   343.6 1101.99   352.1 1105.69   363.9 1112.67
   376.1 1117.26   392.3 1122.49   420.7 1128.98     445 1136.89   457.2 1142.17
   481.5 1155.02   501.8 1160.22   509.9 1163.35   526.1 1174.61   543.1 1181.47
#Mann= 6 ,-1,0
       0      .1       0     150     .06       0     250     .05       0
   250.3    .045       0   266.6     .05       0     350      .1       0
Bank Sta=250.3,266.6
XS Rating Curve= 0 ,0
Exp/Cntr(USF)=0,0
Exp/Cntr=0.3,0.1

Type RM Length L Ch R = 1 ,9407    ,73.3,73.5,73.8
BEGIN DESCRIPTION:
Structure XS 2
END DESCRIPTION:
XS GIS Cut Line= 2
1693971.49424825442300.394778883  1693434.347489442382.705246614
#Sta/Elev= 30
       0 1196.85    23.7 1185.46    43.9 1179.57    72.2  1164.7   108.6 1154.15
   120.8 1147.69     137  1135.9   145.1 1132.07   157.2 1128.47   173.4 1125.95
   185.6 1122.61   205.8 1114.66   217.9 1112.33     226 1107.43   234.1 1097.35
   238.1 1094.52   254.3 1094.46   263.9 1091.82   270.5 1089.98   274.5 1091.73
   282.6 1093.43   331.2 1096.46   343.5 1101.79   375.7 1118.25   432.4 1134.29
   476.8 1155.58   504.9 1165.95   529.4 1179.07   537.6 1181.86   543.4 1182.71
#Mann= 6 ,-1,0
       0      .1       0     150     .06       0     250     .05       0
   263.9    .045       0   274.5     .05       0     350      .1       0
Bank Sta=263.9,274.5
XS Rating Curve= 0 ,0
Exp/Cntr(USF)=0,0
Exp/Cntr=0.3,0.1

Type RM Length L Ch R = 1 ,9333    ,82.8,82.6,82.2
BEGIN DESCRIPTION:
Structure XS 1
END DESCRIPTION:
XS GIS Cut Line= 2
1693966.52723726442240.081074079  1693435.057062442295.427767899
#Sta/Elev= 30
       0 1194.14    22.5 1184.66    50.7 1176.04    74.8 1164.01     111  1154.3
   119.1  1150.5   135.1  1139.2   143.2 1134.86   175.4 1126.33   206.6 1115.01
   219.6 1108.16   231.7    1106   235.7 1103.04   239.7 1098.14   243.7 1094.86
   259.8  1093.7   264.9 1090.97   271.9 1089.53  277.751090.898   283.9 1092.51
   315.9 1092.28   336.2 1095.28   372.4 1117.08   420.7 1131.67   432.7 1136.45
   448.8 1147.18   464.9    1156   490.7 1165.56   521.2 1181.85   534.3 1187.72
#Mann= 6 ,-1,0
       0      .1       0     140     .06       0     240     .05       0
   264.9    .045       0  277.75     .05       0     340      .1       0
Bank Sta=264.9,277.75
XS Rating Curve= 0 ,0
Exp/Cntr(USF)=0,0
Exp/Cntr=0.3,0.1

Type RM Length L Ch R = 1 ,9251    ,66.8,70.4,77.8
BEGIN DESCRIPTION:
Structure XS 4
END DESCRIPTION:
XS GIS Cut Line= 3
1693965.81766427 442221.632176141693725.98199105442180.476942274
1693429.38047802 442224.47046813
#Sta/Elev= 30
       0 1194.19      18 1186.62    42.3 1179.64    57.8 1172.18    78.8 1163.94
   111.3 1154.24   119.4 1149.85   127.5 1143.93   135.7 1141.94   147.8 1135.48
   164.1 1130.28   188.4 1125.44   224.9 1111.75   233.1 1107.58   245.2 1099.14
   253.3 1097.43   261.4 1091.41   273.5 1091.56   280.3 1089.52   285.7 1088.38
  291.461089.547   326.1 1090.56   342.3  1092.5   350.4 1096.64   382.7 1117.69
   435.3 1136.64   459.5 1150.72   492.4 1162.68   520.9 1177.08   543.2 1189.62
#Mann= 5 ,-1,0
       0      .1       0     240     .06       0   280.3    .045       0
  291.46     .06       0  343.34      .1       0
Bank Sta=280.3,291.46
XS Rating Curve= 0 ,0
Exp/Cntr(USF)=0,0
Exp/Cntr=0.3,0.1

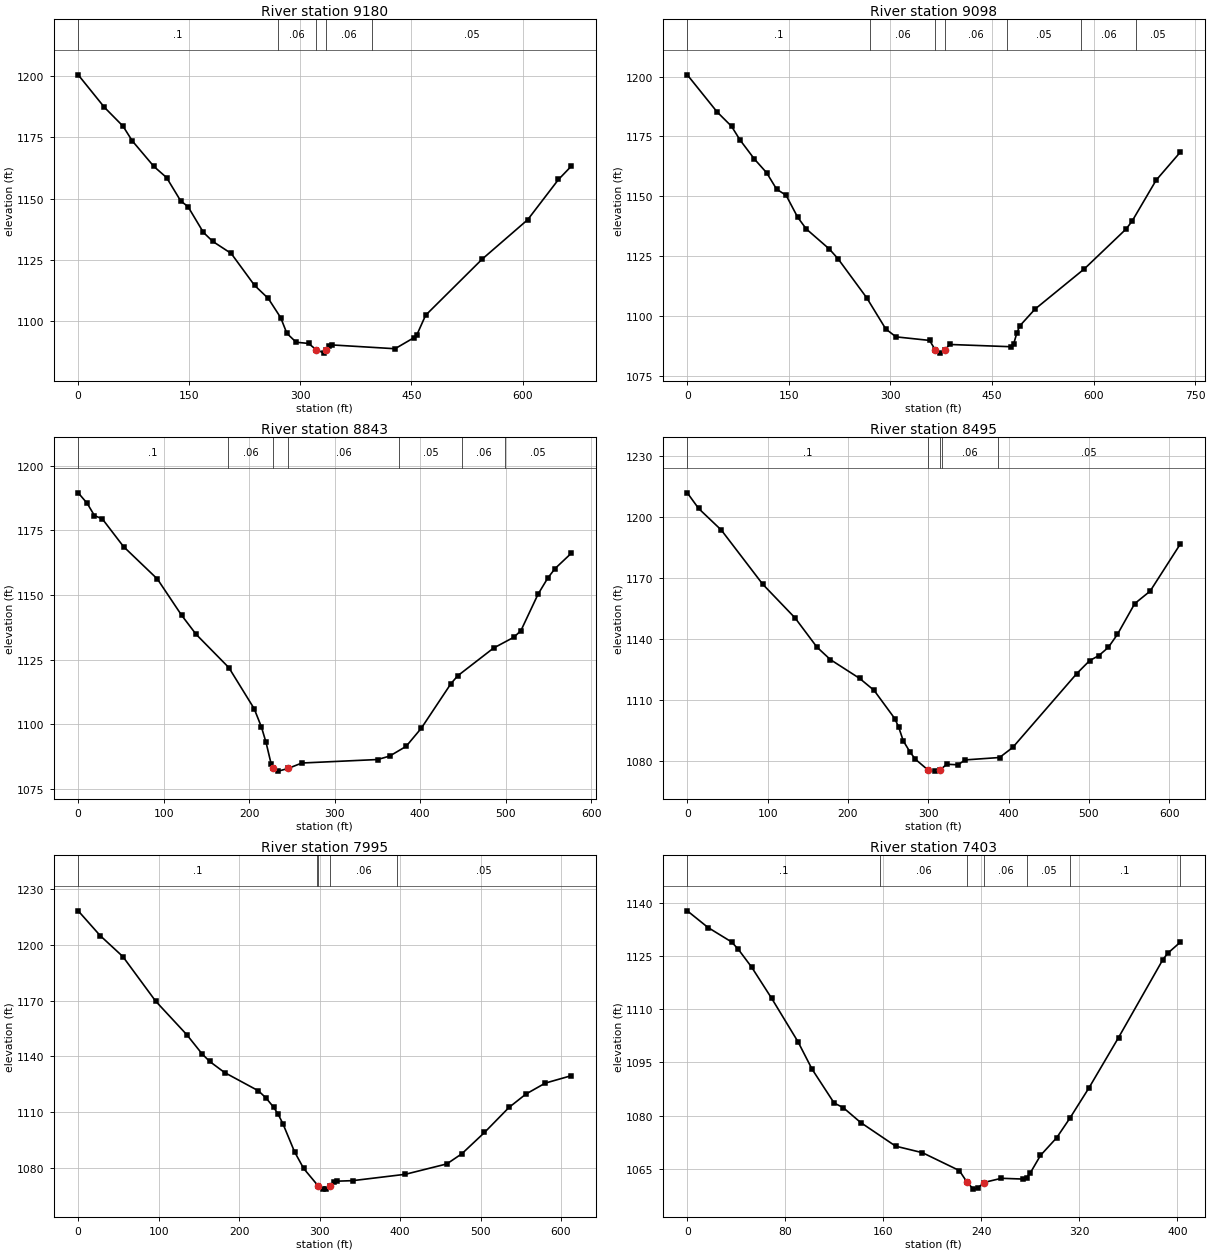
Type RM Length L Ch R = 1 ,9180    ,81.2,82.2,79.2
BEGIN DESCRIPTION:
Structure XS 3
END DESCRIPTION:
XS GIS Cut Line= 6
1693982.02006772 442215.128243671693679.03239771442124.302899966
1693654.90691579442098.0486990511693633.61972586442058.312611181
1693615.17082792442001.5467713661693429.26270253442096.629553056
#Sta/Elev= 30
       0 1200.46    35.4 1187.22    60.5 1179.55      73 1173.56   102.2 1163.13
   119.3 1158.61   138.5 1149.04   148.2 1146.79     169 1136.28   181.6 1132.61
   206.6 1127.68   238.1 1114.69   256.7 1109.33   273.4 1101.53   281.8 1095.12
   294.3 1091.51     311 1091.02   321.4 1088.45   332.3 1087.07   334.81088.473
     338 1090.03   343.2  1090.4   427.8 1088.86   453.5 1093.38   456.9 1094.27
   469.1  1102.5   545.5 1125.38   606.9 1141.42   648.5 1157.82   665.5 1163.14
#Mann= 5 ,-1,0
       0      .1       0     270     .06       0   321.4    .045       0
   334.8     .06       0  397.04     .05       0
Bank Sta=321.4,334.8
XS Rating Curve= 0 ,0
Exp/Cntr(USF)=0,0
Exp/Cntr=0.3,0.1

Type RM Length L Ch R = 1 ,9098    ,264.1,255.3,243.1
BEGIN DESCRIPTION:
Structure XS 2
END DESCRIPTION:
XS GIS Cut Line= 6
1693985.56793271442200.9367837161693709.54403661442102.306137037
1693679.74197071442044.1211512271693656.32606179442027.091399283
1693642.13460183441954.0053805211693404.42764761442073.213644132
#Sta/Elev= 30
       0 1200.75      44 1185.25    65.3 1179.25      78 1173.48    99.2 1165.52
   117.2 1159.82   131.9 1152.96     146 1150.39     163 1141.24   175.7 1136.34
   209.7 1127.96   222.4 1123.96   264.9  1107.6   293.1 1094.55   308.2 1091.23
   357.9 1089.74   366.6  1085.6     373 1084.43  379.911085.566   387.6 1088.05
   477.7 1087.11   482.2 1088.41   486.7 1092.79   491.1 1095.82   513.5  1102.8
   586.6 1119.68   647.8 1136.22   656.7 1139.46   692.5 1156.72     728 1168.36
#Mann= 7 ,-1,0
       0      .1       0     270     .06       0   366.6    .045       0
  379.91     .06       0  472.03     .05       0  582.03     .06       0
  662.03     .05       0
Bank Sta=366.6,379.91
XS Rating Curve= 0 ,0
Exp/Cntr(USF)=0,0
Exp/Cntr=0.3,0.1

Type RM Length L Ch R = 1 ,8843    ,346.8,348.1,348.8
BEGIN DESCRIPTION:
Structure XS 1
END DESCRIPTION:
XS GIS Cut Line= 4
1693786.42463201441619.9591730561693680.53038515441732.776288131
1693528.62682539441897.7260041941693374.66742013442021.269218184
#Sta/Elev= 30
       0 1189.55    10.5  1185.5      19 1180.74    28.2 1179.47      53 1168.75
    92.6  1156.2   120.9 1142.19   137.9 1134.79   176.2  1121.9   205.8 1106.01
   214.3 1098.91   219.7 1092.93   225.6  1084.7   228.31082.922   234.1 1081.85
   245.4 1082.88   261.6 1084.99   350.2 1086.34   364.3 1087.68   383.5 1091.44
   401.3 1098.47     436 1115.75   443.9 1118.76   485.7 1129.46   509.4 1133.65
   517.7 1136.19   537.8 1150.34   549.2 1156.59   557.7 1160.25   576.4 1166.09
#Mann= 7 ,-1,0
       0      .1       0  174.73     .06       0   228.3    .045       0
   245.4     .06       0  374.73     .05       0  448.97     .06       0
  498.97     .05       0
Bank Sta=228.3,245.4
XS Rating Curve= 0 ,0
Exp/Cntr(USF)=0,0
Exp/Cntr=0.3,0.1

Type RM Length L Ch R = 1 ,8495    ,498.5,499.7,500.4
XS GIS Cut Line= 6
  1693569.980838441390.504984096  1693437.303938441514.508345008
1693381.34046726441564.6129035951693303.63458592441627.558643833
1693248.51002426441678.6648408321693122.46631309441809.704276919
#Sta/Elev= 30
       0  1212.1    14.1 1204.39    42.4 1193.74    93.9 1167.08   134.2 1150.46
   161.4 1136.09   178.2 1129.93   214.6 1120.67   232.6 1114.77   258.3 1100.89
   263.2 1096.69   268.9 1089.91   277.4 1084.34     284 1080.85   299.5 1075.61
   308.7 1074.99   314.9 1075.59     323 1078.38   337.2  1078.1   345.8 1080.51
   388.8  1081.7   405.2 1086.65     485 1123.08   500.9 1129.41   512.4 1131.91
   524.2 1135.94   535.5 1142.32   557.1 1157.52   576.3 1163.67   613.7 1186.77
#Mann= 5 ,-1,0
       0      .1       0   299.5    .045       0   314.9      .1       0
  316.72     .06       0  386.72     .05       0
Bank Sta=299.5,314.9
XS Rating Curve= 0 ,0
Exp/Cntr(USF)=0,0
Exp/Cntr=0.3,0.1

Type RM Length L Ch R = 1 ,7995    ,594.3,592,588.3
XS GIS Cut Line= 6
1693291.56144734441050.5112415111693136.67888309441144.654425919
1693072.58977242441183.6103847621692987.13685934441235.551225752
1692848.27690084 441319.955912591692768.16518442441368.650697082
#Sta/Elev= 30
       0 1218.34    27.4 1204.96    55.5 1193.72    96.3  1169.7     135 1151.64
   153.8 1141.42   163.2 1137.33   181.9  1131.3     224 1121.45   233.4 1117.61
   242.8 1112.66   248.5 1108.84   254.4 1103.75   268.9  1088.6   280.2 1079.65
  298.381070.202   303.9 1068.54   308.3 1068.69     313  1070.2   317.7 1072.29
   321.3 1072.82   341.1  1073.1   406.6 1076.53   458.1 1082.11   476.8 1087.59
   504.9 1099.03   535.3 1112.49   556.4 1119.71   580.4  1125.6   612.5 1129.57
#Mann= 5 ,-1,0
       0      .1       0  296.25     .06       0  298.38    .045       0
     313     .06       0  396.25     .05       0
Bank Sta=298.38,313
XS Rating Curve= 0 ,0
Exp/Cntr(USF)=0,0
Exp/Cntr=0.3,0.1

Type RM Length L Ch R = 1 ,7403    ,70.6,71.9,73.3
BEGIN DESCRIPTION:
Structure XS 4
END DESCRIPTION:
XS GIS Cut Line= 4
1692850.65337594440559.1559263711692735.20970155440666.025618573
1692666.29972546440770.0510666251692586.78642674440860.090866974
#Sta/Elev= 30
       0 1137.82    16.9 1133.11    36.2 1129.02    41.6 1126.96    52.5 1121.92
    68.9 1113.07    90.4  1100.8   101.8  1093.1   119.8 1083.54   127.3 1082.21
   141.5 1078.02     170 1071.35   191.9  1069.5     222 1064.45  228.391061.102
   233.5 1059.21   237.1 1059.46   241.9 1061.07   256.3 1062.27   273.9 1062.05
   276.8 1062.44   279.7 1063.67   288.2 1068.73   301.4 1073.72   312.1  1079.2
   327.7 1087.77   351.9 1102.02   388.1 1124.06   392.1 1125.85   402.2 1128.93
#Mann= 7 ,-1,0
       0      .1       0  157.32     .06       0  228.39    .045       0
   241.9     .06       0  277.32     .05       0   312.1      .1       0
   402.1     .05       0
Bank Sta=228.39,241.9
XS Rating Curve= 0 ,0
Exp/Cntr(USF)=0,0
Exp/Cntr=0.3,0.1

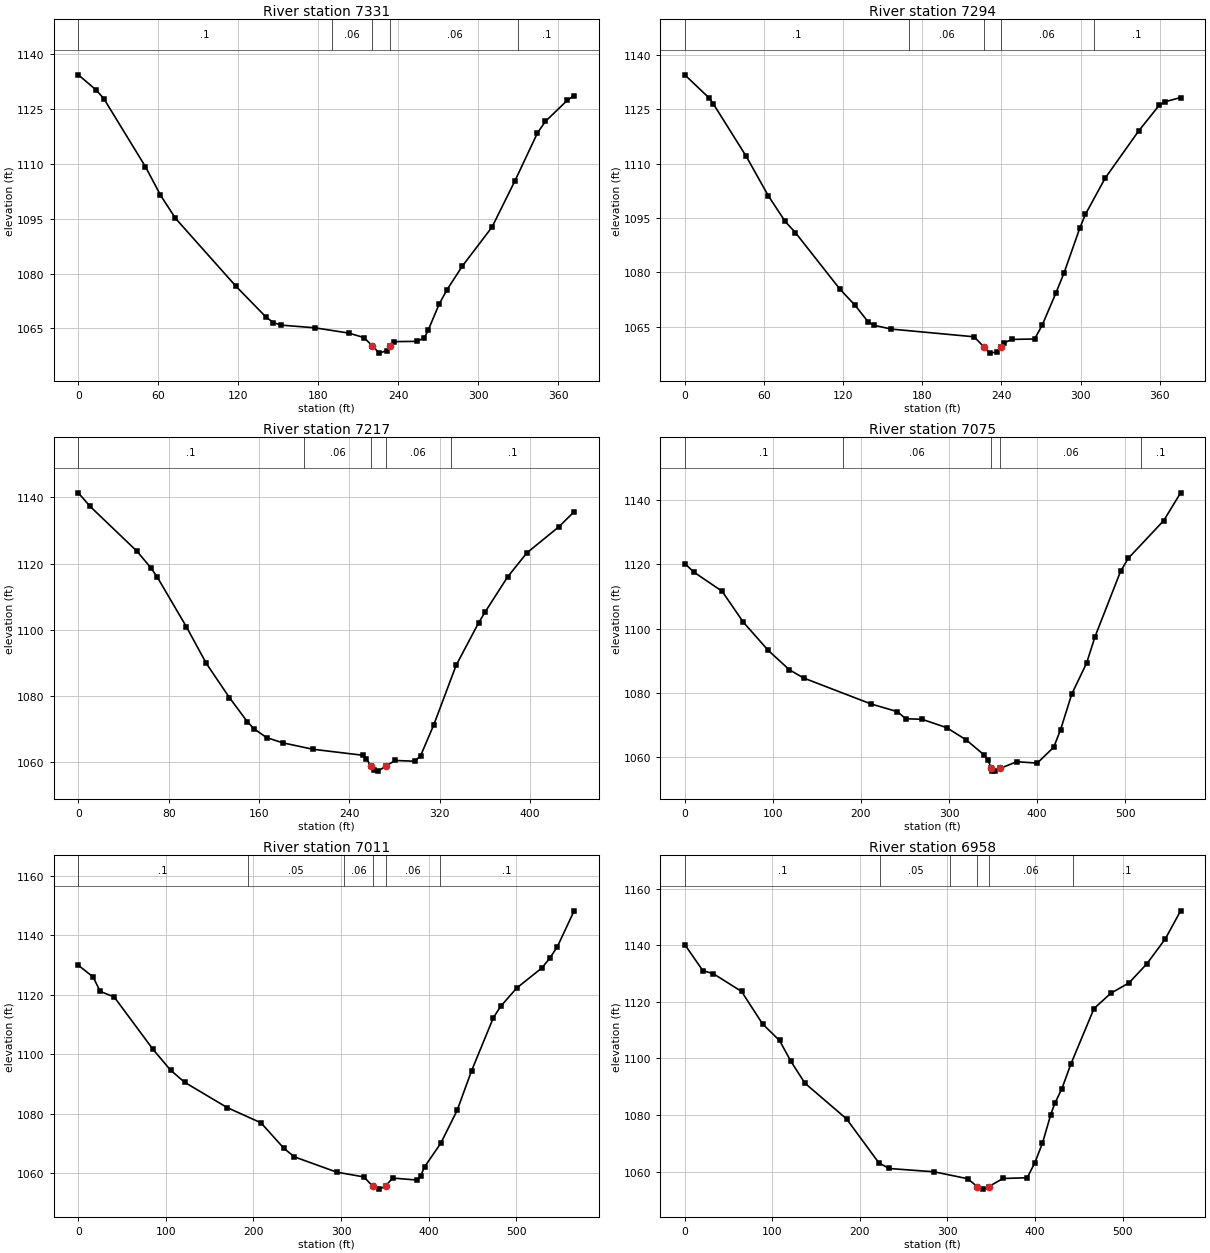
Type RM Length L Ch R = 1 ,7331    ,36.8,37,36.9
BEGIN DESCRIPTION:
Structure XS 3
END DESCRIPTION:
XS GIS Cut Line= 2
1692791.44115446440532.9146195951692528.89914532440796.166201736
#Sta/Elev= 30
       0 1134.33    13.4 1130.17    19.1 1127.83    50.3 1109.22    61.6 1101.45
    72.8 1095.12     118 1076.61   140.7 1068.12   146.3 1066.59     152 1065.91
   177.4 1065.17   202.8 1063.73   214.1 1062.51  220.481060.247   225.6 1058.25
   231.1 1058.91     234 1060.23     237 1061.39   253.9 1061.47   259.5 1062.45
   262.3 1064.48   270.6 1071.67   276.3 1075.49   287.9 1082.02   310.2  1092.7
   327.4 1105.35   344.3 1118.45   350.2 1121.58   366.7 1127.38   371.8 1128.65
#Mann= 5 ,-1,0
       0      .1       0     190     .06       0  220.48    .045       0
     234     .06       0     330      .1       0
Bank Sta=220.48,234
XS Rating Curve= 0 ,0
Exp/Cntr(USF)=0,0
Exp/Cntr=0.3,0.1

Type RM Length L Ch R = 1 ,7294    ,78.3,77.6,76.7
BEGIN DESCRIPTION:
Structure XS 2
END DESCRIPTION:
XS GIS Cut Line= 2
1692769.44439153440507.3699916781692500.51622541440769.912000822
#Sta/Elev= 30
       0 1134.44    18.6    1128    21.6 1126.46    46.6 1111.96    63.3 1101.12
    76.1 1094.04    83.8 1090.99   117.7 1075.34   129.1 1070.94   139.1 1066.32
   143.2 1065.47   156.3 1064.41   219.3 1062.28  226.611059.518   231.1 1057.78
   236.4  1058.1   239.4  1059.5   242.2 1060.63   247.8 1061.56   265.1 1061.67
   270.8  1065.4   281.4 1074.46   287.5 1079.93   299.4 1092.24   303.7 1096.05
   318.6 1105.98     344 1118.98   359.6 1126.06   363.8    1127   375.8 1128.19
#Mann= 5 ,-1,0
       0      .1       0     170     .06       0  226.61    .045       0
   239.4     .06       0     310      .1       0
Bank Sta=226.61,239.4
XS Rating Curve= 0 ,0
Exp/Cntr(USF)=0,0
Exp/Cntr=0.3,0.1

Type RM Length L Ch R = 1 ,7217    ,141.8,141.1,140.5
BEGIN DESCRIPTION:
Structure XS 1
END DESCRIPTION:
XS GIS Cut Line= 2
1692714.09769771440408.0297720021692439.49294761440750.753529884
#Sta/Elev= 30
       0  1141.4    10.3 1137.34    51.9 1123.77    64.4 1118.68    70.1 1115.84
    95.7 1100.95   113.4 1089.85   133.9 1079.51   149.7 1072.27   155.4 1070.17
   166.8 1067.47     181 1065.89   207.9 1063.94   251.8 1062.14     255 1061.14
  259.331058.798   262.1 1057.69   265.5 1057.34   272.1 1058.79   280.6 1060.56
   297.9 1060.33   303.1 1061.93   314.8 1071.27   334.7 1089.34   354.6 1102.16
   360.3 1105.39   380.2 1115.97   397.3 1123.26   425.8 1131.18   439.2 1135.71
#Mann= 5 ,-1,0
       0      .1       0     200     .06       0  259.33    .045       0
   272.1     .06       0     330      .1       0
Bank Sta=259.33,272.1
XS Rating Curve= 0 ,0
Exp/Cntr(USF)=0,0
Exp/Cntr=0.3,0.1

Type RM Length L Ch R = 1 ,7075    ,64.2,64.1,64.3
BEGIN DESCRIPTION:
Structure XS 4
END DESCRIPTION:
XS GIS Cut Line= 4
1692527.47999932440194.448299698 1692502.6449444 440420.80208596
1692399.75685974440591.8091784031692330.21870597440708.179150023
#Sta/Elev= 30
       0 1120.28    10.1 1117.64    42.3 1111.65    66.5 1101.99    94.7 1093.22
   118.8 1087.17   134.9 1084.62   211.3 1076.55   241.4 1074.13   250.7 1071.94
   269.4 1071.76   297.4 1069.14   319.7 1065.29   339.4 1060.74   344.1 1059.13
  347.651056.567   348.8 1055.73   351.8 1055.62   358.1 1056.49   376.8 1058.55
   400.1 1058.12   418.8 1063.09   426.6 1068.58   439.2 1079.61   456.1 1089.29
   465.6 1097.47   494.6 1117.83   503.4 1121.91   543.6 1133.65   562.8  1142.3
#Mann= 5 ,-1,0
       0      .1       0     180     .06       0  347.65    .045       0
   358.1     .06       0  517.29      .1       0
Bank Sta=347.65,358.1
XS Rating Curve= 0 ,0
Exp/Cntr(USF)=0,0
Exp/Cntr=0.3,0.1

Type RM Length L Ch R = 1 ,7011    ,53.5,53.6,53.6
BEGIN DESCRIPTION:
Structure XS 3
END DESCRIPTION:
XS GIS Cut Line= 3
1692486.19444746440183.7689915991692470.71415951440336.362899236
1692271.67535209440698.172642917
#Sta/Elev= 30
       0 1129.95    16.9 1126.01    24.9 1121.18      41 1119.27    85.2 1101.71
   105.3 1094.69   121.4  1090.6   170.1 1082.08   208.6 1076.97   234.9 1068.36
   246.7 1065.53   295.1 1060.38   326.2 1058.77   336.2 1055.65   343.9 1054.67
  350.831055.675     359 1058.39   386.4 1057.73     391 1059.14   395.5 1062.19
   413.8 1070.02   432.6 1081.12   449.2 1094.53   474.1 1112.36   482.4 1116.15
   500.5 1122.24   529.5 1129.07   538.3 1132.26   547.1 1136.19   566.3 1148.26
#Mann= 6 ,-1,0
       0      .1       0  193.38     .05       0  303.38     .06       0
   336.2    .045       0  350.83     .06       0  413.38      .1       0
Bank Sta=336.2,350.83
XS Rating Curve= 0 ,0
Exp/Cntr(USF)=0,0
Exp/Cntr=0.3,0.1

Type RM Length L Ch R = 1 ,6958    ,255.7,258.4,260
BEGIN DESCRIPTION:
Structure XS 2
END DESCRIPTION:
XS GIS Cut Line= 3
1692438.18782665440160.0523953131692422.70753869 440312.64630295
1692223.66873128440674.456046631
#Sta/Elev= 30
       0 1140.25    20.6 1131.06    32.7 1129.95    64.8 1123.69    88.9 1112.17
   108.2 1106.35   121.1 1099.02   137.2 1091.25   184.7 1078.64   221.7 1063.05
   233.4 1061.09   284.8 1059.91   323.1 1057.47  334.241054.621   340.4 1053.79
347.02781054.629   363.3 1057.55   391.1 1057.82   399.8 1063.14   408.5 1070.06
     418 1080.16   422.6 1084.12   430.7 1089.33   440.9 1097.99   467.4 1117.66
   486.5 1123.04   507.3 1126.71   527.6 1133.42   548.8 1142.27   566.3  1152.2
#Mann= 6 ,-1,0
       0      .1       0  223.38     .05       0  303.38     .06       0
  334.24    .045       0347.0278     .06       0  443.38      .1       0
Bank Sta=334.24,347.0278
XS Rating Curve= 0 ,0
Exp/Cntr(USF)=0,0
Exp/Cntr=0.3,0.1