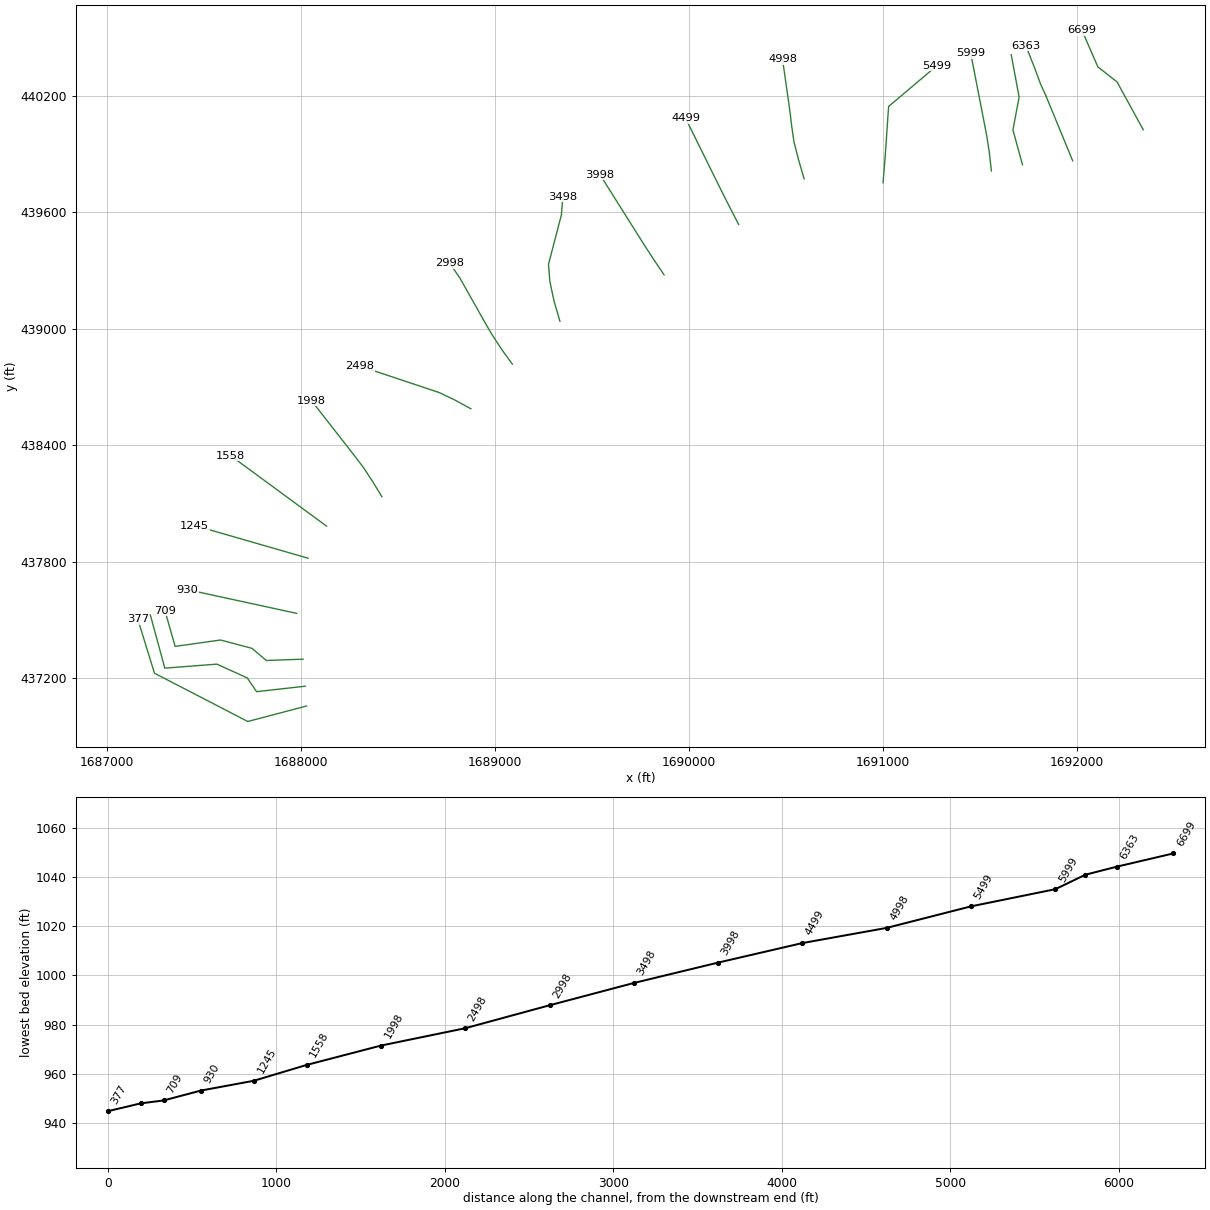
HEC-RAS study BROWNSRN.prj: BROWNSRN

--- BROWNSRN.g01 (geometry) --- (continued)

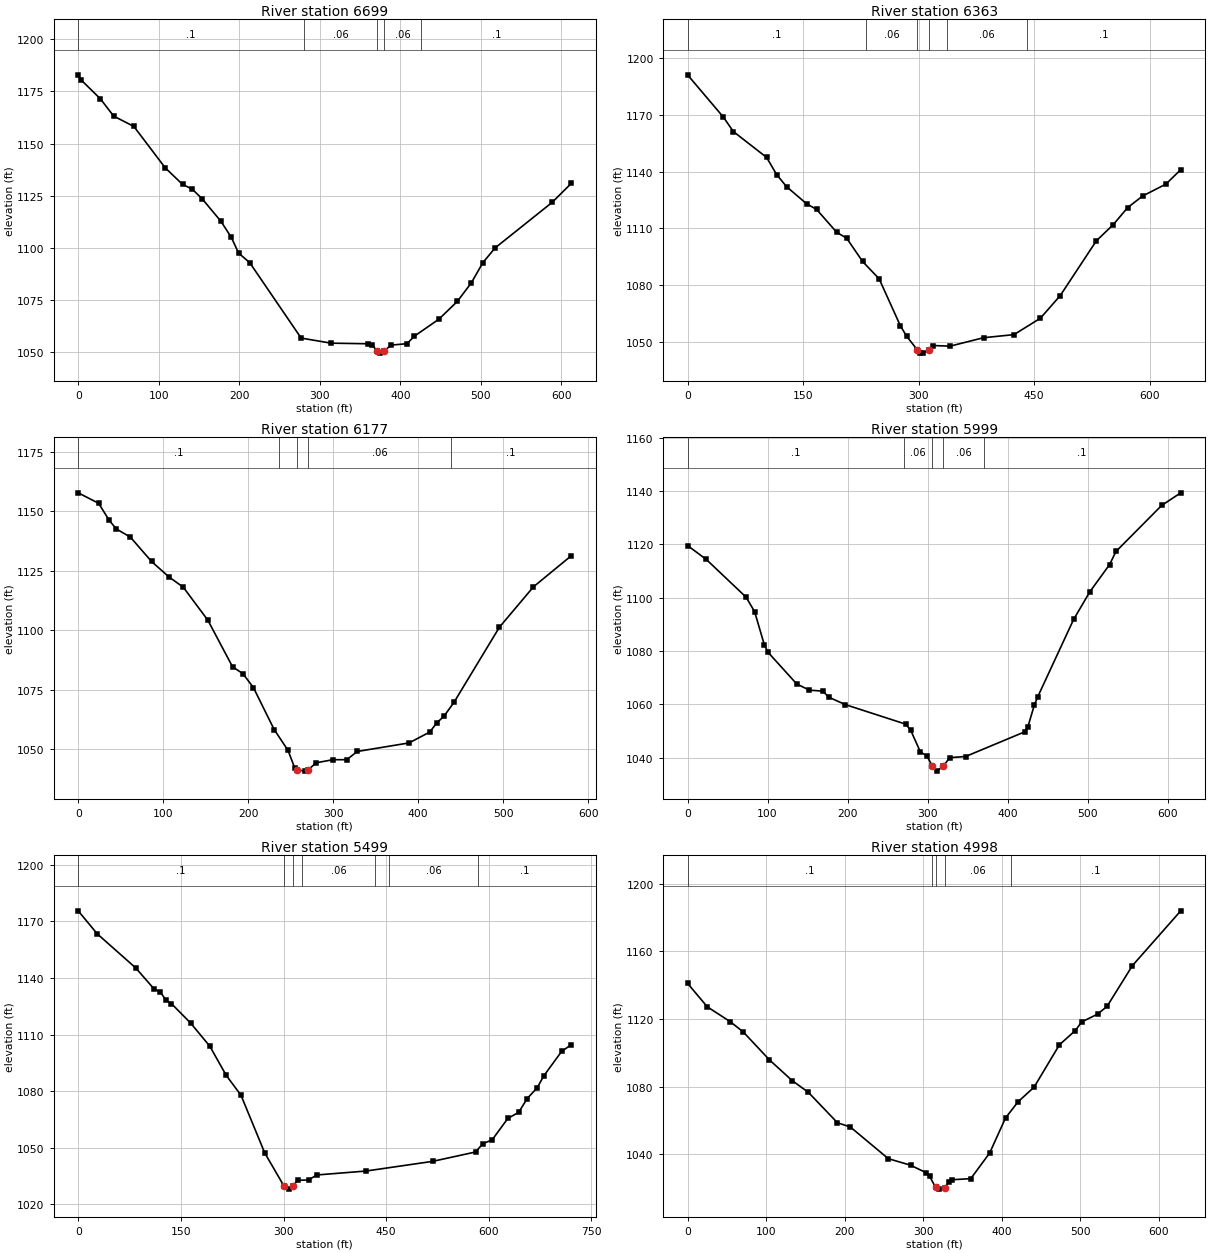
Type RM Length L Ch R = 1 ,6699    ,338.5,336.4,332.6
BEGIN DESCRIPTION:
Structure XS 1
END DESCRIPTION:
XS GIS Cut Line= 4
1692341.31640703440025.8311769061692206.12874553440272.413471484
1692107.71212796440349.2000632161692025.51802977440538.462789317
#Sta/Elev= 30
       0 1182.94     3.1 1180.68    27.5 1171.45    44.1 1163.14    69.1 1158.21
     108 1138.39   129.6 1130.41   141.4 1128.21   153.6 1123.66   177.2 1112.76
   190.1 1105.04   199.2 1097.48   212.9 1092.96   276.8 1056.78   313.9 1054.35
   359.9 1054.06   365.4 1053.39   371.1 1050.56   375.1 1049.57  380.141050.583
   388.2  1053.4   408.3  1054.1   417.4  1057.7   447.8 1065.82   470.7 1074.35
   488.2 1083.29   502.5 1092.97   517.7 1100.01   588.5 1121.83   612.4 1130.99
#Mann= 5 ,-1,0
       0      .1       0     280     .06       0   371.1    .045       0
  380.14     .06       0  426.04      .1       0
Bank Sta=371.1,380.14
XS Rating Curve= 0 ,0
Exp/Cntr(USF)=0,0
Exp/Cntr=0.3,0.1

Type RM Length L Ch R = 1 ,6363    ,190.1,185.8,182.2
XS GIS Cut Line= 6
1691977.85217888439865.5314112441691880.28249213440102.479100077
1691842.20612472440194.9464348241691811.49096305440263.408240153
1691780.08165097440348.4185549581691736.32277856440458.459340705
#Sta/Elev= 30
       0 1191.01    46.5 1168.72    59.5 1161.09   102.7 1147.42   115.7 1138.37
   128.7 1131.94   154.7 1122.95   167.6 1119.98   193.6 1107.94   206.6  1104.8
   227.3 1092.52   248.8 1083.34   276.3 1058.61   284.4  1053.1  298.081046.008
   301.7 1044.31   306.1 1044.17   313.1 1045.98     319 1048.18   340.7 1047.84
   384.3  1052.3   423.8 1053.93   458.1  1062.6   483.7 1074.44   530.7  1103.4
   552.8 1112.02   571.3 1120.94   590.9 1127.09     621 1133.34   640.3 1140.97
#Mann= 6 ,-1,0
       0      .1       0  231.25     .06       0  298.08    .045       0
   313.1      .1       0  336.25     .06       0  441.29      .1       0
Bank Sta=298.08,313.1
XS Rating Curve= 0 ,0
Exp/Cntr(USF)=0,0
Exp/Cntr=0.3,0.1

Type RM Length L Ch R = 1 ,6177    ,176.7,178.8,181.8
XS GIS Cut Line= 4
1691719.12720177439845.3533900471691669.93965045440024.743283091
1691701.76688954440194.0063273341691661.25949433440412.456922896
#Sta/Elev= 30
       0 1157.75      24 1153.37    36.5  1146.2    44.8 1142.61    61.4 1139.15
    86.3 1128.93     107 1122.38   123.6 1118.15   152.6 1104.25   181.6 1084.73
   193.9  1081.8   206.2 1075.98   230.6 1058.37   246.9 1049.62     255 1042.04
  257.15 1041.51   266.5 1040.91  270.62 1041.51   280.2 1044.42   299.8 1045.71
     316  1045.7   328.3 1049.16   389.3 1052.75   413.7 1057.32   421.8 1061.12
   430.5    1064   442.2 1069.79   495.7 1101.35   535.7 1118.28   580.4 1131.39
#Mann= 5 ,-1,0
       0      .1       0  236.01     .06       0  257.15    .045       0
  270.62     .06       0  438.24      .1       0
Bank Sta=257.15,270.62
XS Rating Curve= 0 ,0
Exp/Cntr(USF)=0,0
Exp/Cntr=0.3,0.1

Type RM Length L Ch R = 1 ,5999    ,501.3,500,497.6
XS GIS Cut Line= 6
1691558.93433517439813.1941623391691548.16893676439908.842593089
1691534.65977742439996.6301471741691520.34615776440070.251719087
1691501.25990984440168.4132681791691452.35154308440419.952791333
#Sta/Elev= 30
       0 1119.55    23.5 1114.32    73.2 1100.19    83.9 1094.71    95.9 1082.42
   100.6 1079.54   136.4 1067.69   152.2 1065.36   168.8    1065   177.1 1062.64
   197.2 1059.94   272.5 1052.63   278.7 1050.44   290.9 1042.25   299.1 1040.68
  305.931036.949   311.3 1035.02   319.5 1036.82   327.6 1040.07   347.5  1040.5
   421.3 1049.74   425.4 1051.74   433.5 1059.92   437.6 1062.87   482.4 1091.84
   502.8 1102.25   527.3 1112.38   535.4 1117.33   592.5 1134.58   616.3 1139.29
#Mann= 5 ,-1,0
       0      .1       0  270.07     .06       0  305.93    .045       0
   319.5     .06       0  370.07      .1       0
Bank Sta=305.93,319.5
XS Rating Curve= 0 ,0
Exp/Cntr(USF)=0,0
Exp/Cntr=0.3,0.1

Type RM Length L Ch R = 1 ,5499    ,499.7,501,502.1
XS GIS Cut Line= 6
1691000.66576667439752.8465140011691008.41903201439846.565814748
1691014.90950459439933.8267950861691026.70705317440108.428479999
1691029.65923303440145.9132816671691279.09449117440356.731926208
#Sta/Elev= 30
       0 1175.63    27.8 1163.42      84 1145.37   110.5 1134.35   120.1 1132.48
   128.1 1128.37   136.1 1126.47   164.2 1116.14   192.3 1103.83   216.3 1088.36
   237.8 1077.88   272.5 1047.29   300.5 1029.77   308.5 1028.05   314.3 1029.88
   320.6 1032.72   336.6  1032.9   348.6 1035.56   420.5 1037.64   517.8 1042.77
   580.7 1047.75   591.1  1052.1   604.9  1054.2   627.8 1065.55   643.5 1068.73
     656 1076.02   670.9 1081.93   680.2 1088.06   706.4 1101.09   720.7  1104.7
#Mann= 7 ,-1,0
       0      .1       0   300.5    .045       0   314.3      .1       0
  326.54     .06       0  434.14      .1       0  454.14     .06       0
  584.14      .1       0
Bank Sta=300.5,314.3
XS Rating Curve= 0 ,0
Exp/Cntr(USF)=0,0
Exp/Cntr=0.3,0.1

Type RM Length L Ch R = 1 ,4998    ,497,499,500.9
XS GIS Cut Line= 6
1690593.97202626439772.3441784231690565.38546926439870.981776416
1690542.03216951439961.7407812631690531.00758526440036.517534584
1690518.84127101440135.7948950831690482.60118601440389.469256505
#Sta/Elev= 30
       0 1141.14    25.2 1127.21    54.3 1118.47      71 1112.34   104.3 1095.83
   133.2 1083.58   153.9 1076.61     191 1058.57   207.3 1056.11   255.8 1037.31
   284.1 1033.46   304.3 1028.93   308.3 1026.98  315.931020.347   320.4 1019.29
   328.4 1020.22   332.5 1023.47   336.5 1024.84   360.8 1025.49   384.9  1040.7
   405.1 1061.43     421 1070.97   441.5 1079.68   473.8 1104.78     494 1113.17
   502.1 1118.26   522.3 1122.89   534.4 1127.47   566.7  1151.6   628.3 1184.05
#Mann= 5 ,-1,0
       0      .1       0     312     .06       0  315.93    .045       0
   328.4     .06       0  412.02      .1       0
Bank Sta=315.93,328.4
XS Rating Curve= 0 ,0
Exp/Cntr(USF)=0,0
Exp/Cntr=0.3,0.1

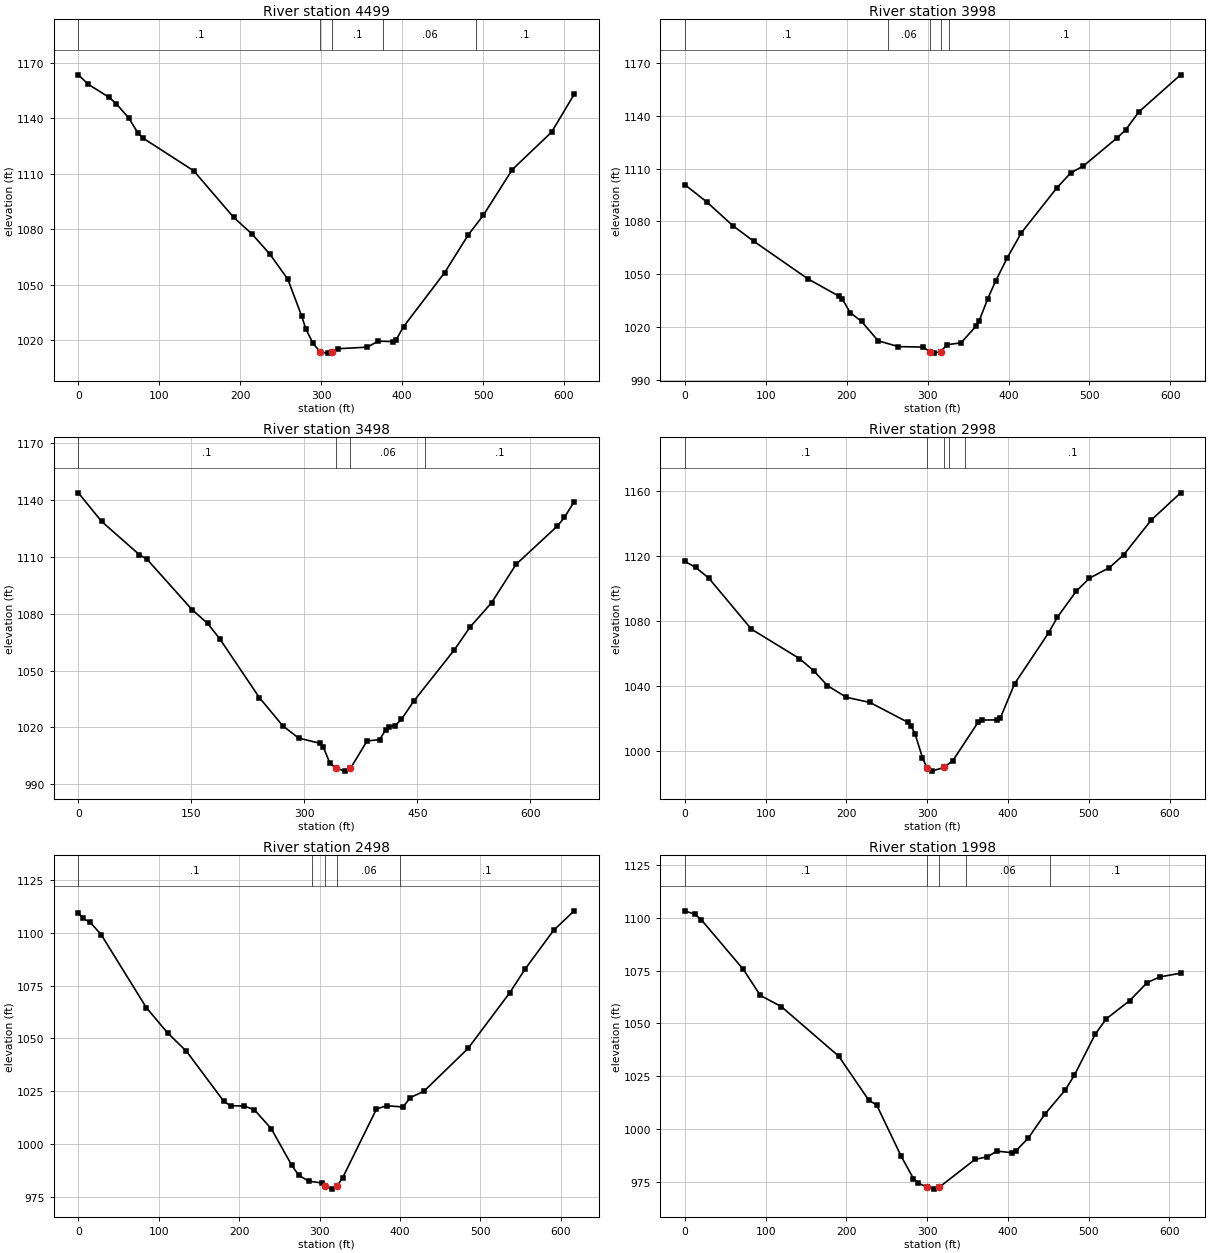
Type RM Length L Ch R = 1 ,4499    ,499.1,500.1,500.6
XS GIS Cut Line= 6
1690256.55898717439537.6737160091690213.65454543439621.043956086
1690173.96532033439699.0313329251690140.70751284439766.254295588
1690024.37342793 440001.568129421689982.82495458440085.608643755
#Sta/Elev= 30
       0 1163.58    12.2  1158.5    38.1 1151.37      47  1147.9    62.2 1140.27
    73.7 1132.12    79.7 1129.43   142.6 1111.67   191.9 1086.51   214.2 1077.67
   236.5 1066.71   258.8 1053.07   275.7  1033.4   281.1 1026.12     290 1018.38
     299 1013.63   307.9 1013.14   312.9 1013.58   321.3 1015.53     357 1016.37
   370.4 1019.62   388.2 1019.37   392.7 1020.47   401.7 1027.41   452.5 1056.66
   481.9 1077.19   500.3 1087.68   536.1 1112.38   584.6  1132.6   612.5 1153.04
#Mann= 5 ,-1,0
       0      .1       0     299    .045       0   312.9      .1       0
  376.27     .06       0  491.27      .1       0
Bank Sta=299,312.9
XS Rating Curve= 0 ,0
Exp/Cntr(USF)=0,0
Exp/Cntr=0.3,0.1

Type RM Length L Ch R = 1 ,3998    ,506.8,500.7,491.3
XS GIS Cut Line= 6
1689872.49217001 439278.094182671689819.88499175439355.756100833
1689772.17905043439429.1184869261689732.21718809 439492.58555159
1689678.93579859439577.2084138391689542.40096667439794.054764926
#Sta/Elev= 30
       0 1100.92    27.1  1091.1    59.6 1077.52    85.1 1068.79     152 1047.42
   190.1 1037.65   194.8 1035.76   204.3 1028.24   218.4 1023.21   238.9 1012.21
     264 1008.89   294.1 1008.65   302.8 1006.03   308.2  1005.2  315.981006.044
   324.1 1009.99   341.3 1011.04   360.2 1020.75   363.7 1023.58   374.4 1036.21
     384 1046.16   398.5 1059.41   415.9 1073.62   459.5 1098.99   476.8 1107.61
   492.6 1111.59   534.3 1127.57   544.6    1132   560.9 1142.22   612.6 1163.32
#Mann= 5 ,-1,0
       0      .1       0  251.31     .06       0   302.8    .045       0
  315.98     .06       0  326.31      .1       0
Bank Sta=302.8,315.98
XS Rating Curve= 0 ,0
Exp/Cntr(USF)=0,0
Exp/Cntr=0.3,0.1

Type RM Length L Ch R = 1 ,3498    ,491.5,499.5,505.6
XS GIS Cut Line= 6
1689335.77342717439038.9306190011689305.59468175439142.534742504
1689284.06355684439243.170368001  1689276.950054439332.512052834
1689343.25930458439586.8379877511689351.27536467439681.412929833
#Sta/Elev= 30
       0 1143.85    30.8 1128.78    80.8 1111.26    91.4 1108.67   150.9  1082.2
   171.5 1074.93   187.7  1066.8   240.3 1035.73   271.5 1020.78   292.4 1014.36
   321.2 1011.56   325.3 1009.51   333.6 1001.42   341.9  998.39   354.3   996.9
  361.25998.3254   383.3 1012.84   399.9 1013.52   408.1  1018.8   412.2 1020.28
   420.5 1020.99   428.8 1024.18   445.3 1033.89     499 1060.85     520 1072.96
   548.5 1085.79     581 1106.04     636 1126.34   645.3 1130.86   658.2 1139.18
#Mann= 4 ,-1,0
       0      .1       0   341.9    .045       0  361.25     .06       0
  460.78      .1       0
Bank Sta=341.9,361.25
XS Rating Curve= 0 ,0
Exp/Cntr(USF)=0,0
Exp/Cntr=0.3,0.1

Type RM Length L Ch R = 1 ,2998    ,494.9,500.2,507.3
XS GIS Cut Line= 6
 1689090.8264105438817.7601295861689035.49482825438894.193047583
1688987.49590851438967.5833207521688949.53830726439032.282666415
1688820.74164884439261.0131800921688767.78079675439338.678707168
#Sta/Elev= 30
       0 1116.67    13.3 1113.03    29.7 1106.38    82.4 1075.05   141.8    1057
   159.3 1049.62   176.5 1040.38   199.8 1033.22   229.1 1030.02   275.7 1017.94
   280.3  1015.3   284.9 1010.81   294.1  996.14   299.4  990.07   305.3  987.85
   320.9990.1281   331.7  994.31   362.9  1017.8   367.5 1019.22   385.9  1019.3
   390.5  1020.5   408.1 1041.48   450.2 1072.76   460.9 1082.25   484.4 1098.35
   500.7 1106.31   525.4  1112.8   543.2 1120.72   577.2 1142.03   613.6 1158.76
#Mann= 5 ,-1,0
       0      .1       0   299.4    .045       0   320.9      .1       0
  327.06     .06       0  347.06      .1       0
Bank Sta=299.4,320.9
XS Rating Curve= 0 ,0
Exp/Cntr(USF)=0,0
Exp/Cntr=0.3,0.1

Type RM Length L Ch R = 1 ,2498    ,503.6,500.3,495.2
XS GIS Cut Line= 6
1688876.99973843438588.0164945871688792.20167968438634.233265668
1688712.10341467438672.2400794181688640.95231026438695.957223594
1688391.92262459438778.9662439231688302.98349801438808.612510085
#Sta/Elev= 30
       0 1109.42     5.6  1106.9    14.7 1104.97    28.3 1099.18    84.7 1064.46
   111.3 1052.42   134.4 1043.89   180.8 1020.17   189.4 1018.05   206.3 1017.93
     219 1016.09     240  1007.1   265.3  989.86     274   985.1   286.4  982.32
   302.5  981.46  307.18979.7764   315.1  978.53   321.4  979.78   328.6  983.88
   370.7 1016.49   383.4 1018.06   403.7 1017.46   412.9 1021.92   429.8 1024.94
   484.6 1045.22   536.5 1071.64   555.4 1082.77   590.9 1101.15   616.5 1110.41
#Mann= 5 ,-1,0
       0      .1       0  290.23     .06       0  307.18    .045       0
   321.4     .06       0  400.23      .1       0
Bank Sta=307.18,321.4
XS Rating Curve= 0 ,0
Exp/Cntr(USF)=0,0
Exp/Cntr=0.3,0.1

Type RM Length L Ch R = 1 ,1998    ,437.9,439.8,441.7
XS GIS Cut Line= 6
1688418.67946084 438134.616482751688369.43087168 438215.31579642
1688320.91095559438288.7634841651688275.41695209438348.425110251
1688213.85408309438427.2284303461688056.09521225438629.159785002
#Sta/Elev= 30
       0  1103.4    12.6 1101.73    20.3 1099.22    72.5 1075.61    93.5 1063.29
   119.5    1058   190.5  1034.5   227.6 1013.72   237.6 1011.29   267.9  987.03
   283.1  976.43   288.2   974.4   299.9  972.47   308.4  971.47   315.3972.4672
   359.3  985.56   374.5   986.8   386.4  989.47   405.4  988.74     410  989.65
   425.3   995.7   445.5 1006.88   470.9 1018.44   482.3 1025.51   507.9 1044.79
   521.7 1052.19   550.7 1060.81   572.4 1069.37   587.7 1072.04   613.8 1073.85
#Mann= 5 ,-1,0
       0      .1       0   299.9    .045       0   315.3      .1       0
  347.59     .06       0  452.59      .1       0
Bank Sta=299.9,315.3
XS Rating Curve= 0 ,0
Exp/Cntr(USF)=0,0
Exp/Cntr=0.3,0.1

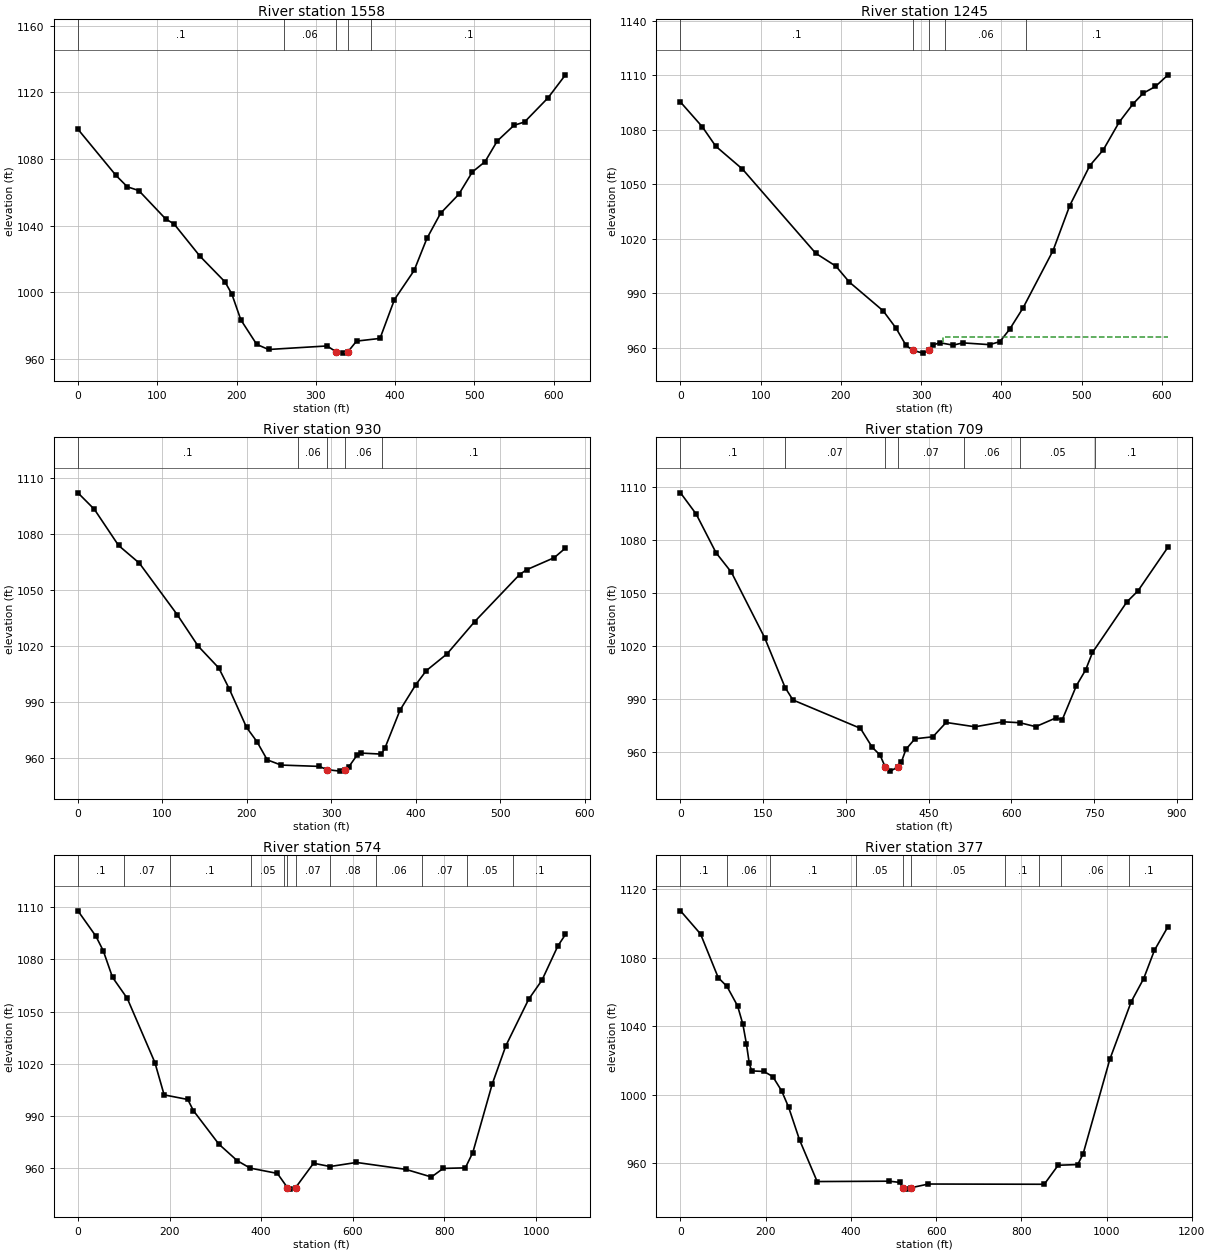
Type RM Length L Ch R = 1 ,1558    ,310.1,313.3,315.7
XS GIS Cut Line= 2
1688133.77254802437983.042338765 1687638.4143403438346.936154084
#Sta/Elev= 30
       0 1097.84      48 1070.14    62.3 1063.31    76.7 1061.09   110.6 1044.07
   121.2 1041.04   153.9  1021.7   185.4 1006.34     194   999.1   205.4  983.58
   225.4  968.88   240.3   965.8   314.1  967.92   325.6  964.42   334.2  963.62
   340.3  964.36   351.3  970.83   380.9  972.44   399.1  995.75   423.9 1013.17
     440 1032.39   457.2 1047.42   480.1 1058.77   497.3  1072.2   513.3 1078.38
   528.7 1090.79   549.8 1100.17   563.1 1102.17   592.7 1116.64   614.7 1130.44
#Mann= 5 ,-1,0
       0      .1       0     260     .06       0   325.6    .045       0
   340.3     .06       0     370      .1       0
Bank Sta=325.6,340.3
XS Rating Curve= 0 ,0
Exp/Cntr(USF)=0,0
Exp/Cntr=0.3,0.1

Type RM Length L Ch R = 1 ,1245    ,313.5,314.4,314.7
XS GIS Cut Line= 2
1688038.25200163437817.9992666521687454.46619569437986.346801388
#Sta/Elev= 30
       0 1095.25    27.2 1081.64    43.9 1070.99    77.2 1058.41   168.6 1012.08
   193.7    1005   210.4  996.27   252.6  980.44   268.7  970.87   281.1  961.42
   289.5  958.75     302  957.19  309.25958.6875   314.4   961.5   322.8  962.93
   339.8  961.59   351.9  962.83   385.2  961.85     398   963.5   410.2  970.29
   426.9  982.04   464.3 1013.58   485.1 1038.31   510.1  1060.3   526.8  1068.9
   546.6 1084.13   564.2 1094.35   576.7 1100.12   591.9 1103.82   607.6 1110.23
#Mann= 5 ,-1,0
       0      .1       0   289.5    .045       0  309.25      .1       0
     330     .06       0     430      .1       0
#XS Ineff= 2 , 0
                           327.1          966.09
Permanent Ineff=
       F       F
Bank Sta=289.5,309.25
XS Rating Curve= 0 ,0
Exp/Cntr(USF)=0,0
Exp/Cntr=0.3,0.1

Type RM Length L Ch R = 1 ,930     ,220.4,221.7,220.7
BEGIN DESCRIPTION:
Structure XS 4
END DESCRIPTION:
XS GIS Cut Line= 2
1687979.14873155437533.9300488161687415.09359871 437656.31079978
#Sta/Elev= 30
       0 1101.93    19.5  1093.1    48.1 1073.81    72.7 1064.36   117.7 1036.74
   142.3 1020.03   166.8 1008.31   179.1  997.21   199.6   976.6   211.9  968.98
   224.1  959.24   240.5  956.44   285.5  955.73   295.3  953.97   310.1   953.2
  316.46953.9281   320.9  955.64   330.6  961.83   334.6  962.86   359.2   962.3
   363.3  965.33   381.4  985.87   400.1  999.47   412.4 1006.88     437 1015.87
   469.7 1033.09   522.9 1058.25   531.1  1060.8   563.9 1067.27   577.2 1072.43
#Mann= 5 ,-1,0
       0      .1       0     260     .06       0   295.3    .045       0
  316.46     .06       0     360      .1       0
Bank Sta=295.3,316.46
XS Rating Curve= 0 ,0
Exp/Cntr(USF)=0,0
Exp/Cntr=0.3,0.1

Type RM Length L Ch R = 1 ,709     ,135.9,134.9,132.8
BEGIN DESCRIPTION:
Structure XS 3
END DESCRIPTION:
XS GIS Cut Line= 6
1688012.48474296437297.6911369131687822.92118774437291.097621949
1687748.74414439437353.7360141091687587.20302777437396.593861376
1687353.13324654437363.6262865551687300.38512683437548.244705553
#Sta/Elev= 30
       0 1106.69    28.4  1094.7    64.4 1072.81    92.4 1061.69   152.5 1024.78
   189.7   996.5   203.9  989.45   326.3   973.4   347.7  962.68   361.8  958.31
   371.5  951.37   380.3  949.18     394951.4525   400.7  954.49   408.8   961.5
   425.1  967.48   457.7  968.61   481.7  976.72   534.1  974.27   585.5   977.1
   615.6  976.56   644.2  974.35   680.9  979.31   692.1  978.14     718   997.6
   734.7 1006.47   747.1 1016.34   809.5 1044.96   829.6  1051.2   884.1    1076
#Mann= 7 ,-1,0
       0      .1       0  189.68     .07       0   371.5    .045       0
     394     .07       0  514.59     .06       0   615.6     .05       0
   752.1      .1       0
Bank Sta=371.5,394
XS Rating Curve= 0 ,0
Exp/Cntr(USF)=0,0
Exp/Cntr=0.3,0.1

Type RM Length L Ch R = 1 ,574     ,197.6,196.7,194.9
BEGIN DESCRIPTION:
Structure XS 2
END DESCRIPTION:
XS GIS Cut Line= 6
1688023.11232684437158.457144247 1687772.5587582 437130.43470565
1687724.75577471437201.3149915151687568.15979431 437272.19527738
1687299.96717064437251.6398435911687225.29701617437526.045603503
#Sta/Elev= 30
       0 1107.94    39.2 1093.39    55.3 1085.01    75.5 1069.74   107.7 1057.63
     168 1020.77   188.2 1002.17   239.8  999.52   252.1   993.1   307.7  973.85
   347.7  964.36   375.8  960.09   435.4  957.03  457.32  948.88   463.8     948
   475.2  948.88   514.4  962.88   550.4  960.99   608.1  963.33   715.6  959.37
   771.7  954.97   797.4   959.9   845.7  960.22     862  969.01   904.3 1008.31
   934.2 1030.42   983.9 1057.09    1013 1068.08  1047.7 1087.75  1064.3 1094.36
#Mann= 12 ,-1,0
       0      .1       0     100     .07       0     200      .1       0
  377.61     .05       0  450.83     .07       0  457.32    .045       0
   475.2     .07       0   550.4     .08       0  650.11     .06       0
  750.11     .07       0  849.89     .05       0  949.89      .1       0
Bank Sta=457.32,475.2
XS Rating Curve= 0 ,0
Exp/Cntr(USF)=0,0
Exp/Cntr=0.3,0.1

Type RM Length L Ch R = 1 ,377     ,,,
BEGIN DESCRIPTION:
Structure XS 1
END DESCRIPTION:
XS GIS Cut Line= 4
 1688029.7058418437056.2576623021687727.38670872436976.775001422
1687246.62795562437225.5060977181687161.01024527437503.133139002
#Sta/Elev= 30
       0 1107.25    47.1 1093.73    88.5 1068.29   109.2 1063.09     134 1051.75
   146.4 1041.09   154.7 1029.68   161.5 1018.15   167.1 1013.81     196 1013.48
   216.7 1010.47   237.4 1002.18   253.9  992.56   279.4  973.58   320.8  949.22
     490  949.43   514.4  948.73   522.9 945.745   528.5   944.8   541.5  945.62
   581.9  947.78   853.9  947.64   886.4  958.73   932.4  959.14     945  965.33
  1007.7 1020.54    1058 1054.22  1087.3 1067.73  1112.4 1084.18  1144.4  1098.1
#Mann= 10 ,-1,0
       0      .1       0     110     .06       0     210      .1       0
  412.59     .05       0   522.9    .045       0   541.5     .05       0
  762.59      .1       0  842.59     .07       0  893.88     .06       0
 1053.88      .1       0
Bank Sta=522.9,541.5
XS Rating Curve= 0 ,0
Exp/Cntr(USF)=0,0
Exp/Cntr=0.3,0.1
LCMann Table=0

Chan Stop Cuts=-1
Use User Specified Reach Order=0
Composite Channel Slope=5